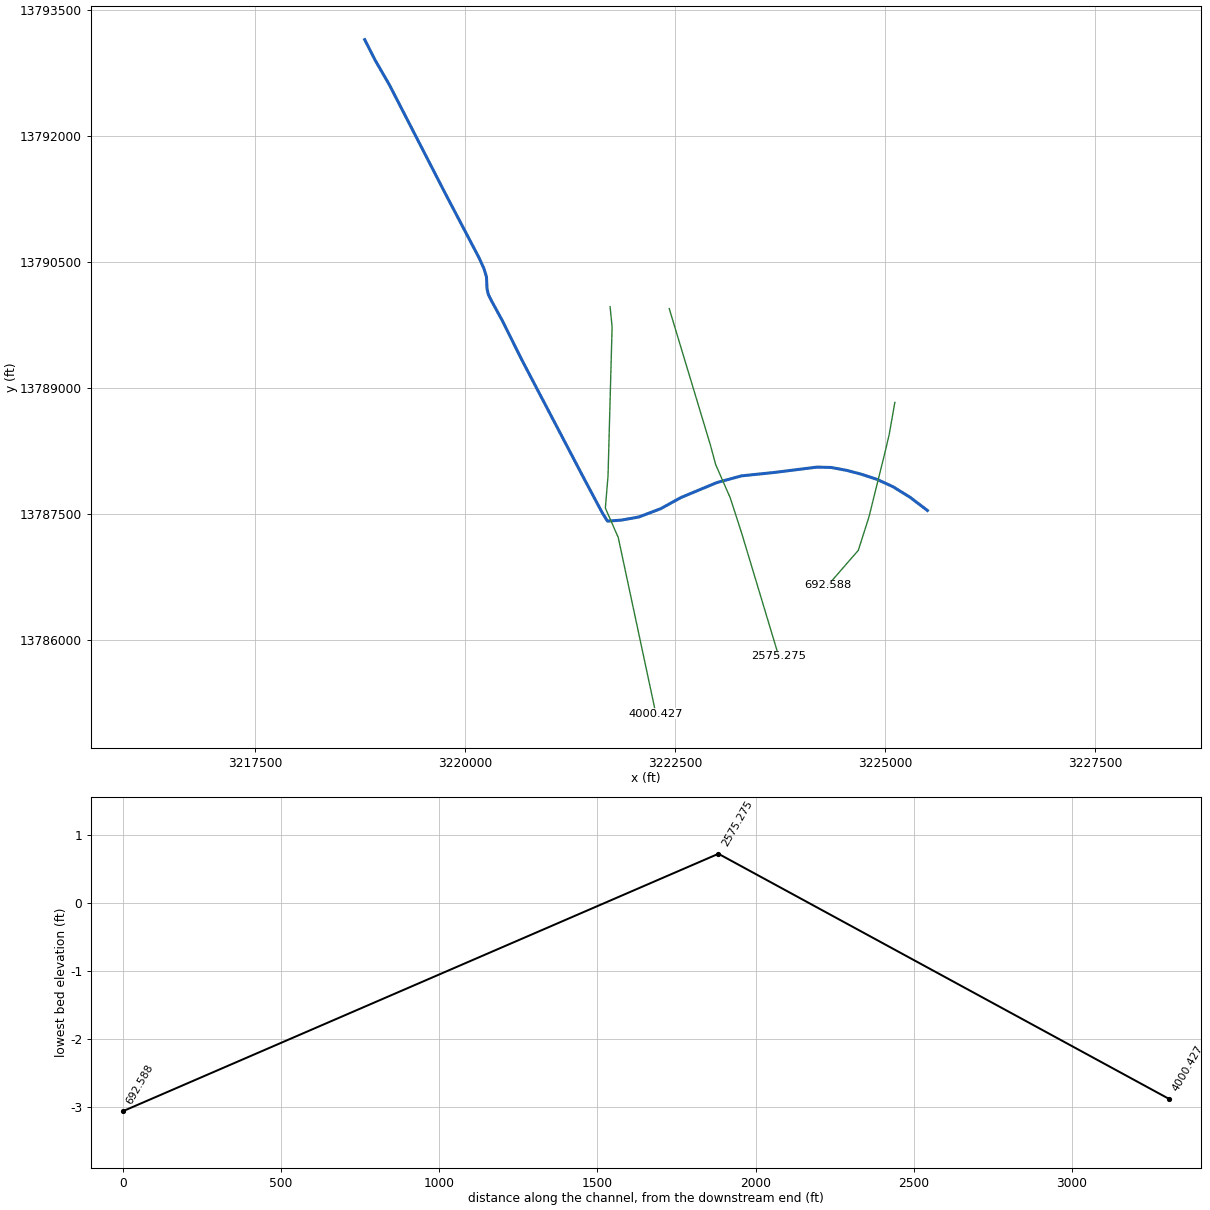
--- A104_04_00.prj (project) ---

Proj Title=A104-04-00
Current Plan=p01
Default Exp/Contr=.3,.1
English Units
Geom File=g01
Geom File=g02
Flow File=f02
Flow File=f01
Plan File=p01
Plan File=p02
Y Axis Title=Elevation
X Axis Title(PF)=Main Channel Distance
X Axis Title(XS)=Station
BEGIN DESCRIPTION:
Clear Creek Basin
Taylor Bayou Tributary 3.10
A104-04-00
Flood Hazard Model
10, 2, 1 & 0.2% Events
Filename: A104_04_00.prj
Prepared by: Perry Vaught	Date: 2-16-04
Reviewed by: __________	Date:
Status (FINAL)
END DESCRIPTION:
DSS Export Rating Curves= 0
DSS Export Rating Curve Sorted= 0
DSS Export Volume Flow Curves= 0
DXF OffsetX= 0
DXF OffsetY= 0
DXF ScaleX= 1
DXF ScaleY= 10

--- A104_04_00.p01 (plan) ---

Plan Title=FEMA Effective June 2007
Version=Version 3.0.1  Mar 2001
Short Identifier=FEMAeff0607
Geom File=g01
Flow File=f01
Subcritical Flow
K Sum by GR= 0
Std Step Tol= 0.003
Critical Tol= 0.003
Num of Std Step Trials= 20
Max Error Tol= 0.1
Flow Tol Ratio= 0.001
Split Flow NTrial= 30
Split Flow Tol= 0.02
Split Flow Ratio= 0.02
Log Output Level= 0
Friction Slope Method= 0
Unsteady Friction Slope Method= 2
Secant Critical Depth
Global Vel Dist= 0 , 0 , 0
Global Log Level= 0
CheckData=True
Encroach Param=-1 ,0,0, 2
Computation Interval=1HOUR
Output Interval=1HOUR
Run HTab= 0
Run UNet= 0
Run PostProcess= 0
UNET Theta= 1
UNET ZTol= 0.02
UNET ZSATol= 0.1
UNET MxIter= 20
UNET MaxInSteps= 20
UNET DtIC= 0
UNET DtMin= 0
UNET MaxCRTS= 20
UNET WFStab= 2
UNET SFStab= 1
UNET WFX= 1
UNET SFX= 1
UNET Convert EG Bridges=-1
UNET Use Existing IB Tables=-1
Instantaneous Interval=1HOUR
Write IC File= 0
Write Velocity= 0
Write Detailed= 0

--- A104_04_00.p02 (plan) ---

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Plan Title=Floodway
Short Identifier=Floodway0607
Geom File=g02
Flow File=f02
Std Step Tol= 0.01
Critical Tol= 0.01
Max Error Tol= 0.3
Encroach River=A104-04-00
Encroach Reach=A104-04-00_0007
Encroach Node=4000.427
       1  4952.9  5047.1
Encroach Node=2575.275
       1    4656    5233
Encroach Node=692.588
       1    4745 5437.79

--- A104_04_00.f01 (steady flow) ---

Flow Title=FEMA Effective June 2007
Version=Version 3.0.1  Mar 2001
Number of Profiles= 4
Profile Names=10PCT_10yr, 2PCT_50yr, 1PCT_100yr, 0.2PCT_500yr
River Rch & RM=A104-04-00,A104-04-00_0007      ,4000.427
     919    1386    1630    2350
River Rch & RM=A104-04-00,A104-04-00_0007      ,2575.275
     986    1488    1749    2523
Boundary for River Rch & Prof#=A104-04-00,A104-04-00_0007      , 1
Up Type= 0
Dn Type= 1
Dn Known WS=2.5
Boundary for River Rch & Prof#=A104-04-00,A104-04-00_0007      , 2
Up Type= 0
Dn Type= 1
Dn Known WS=3.7
Boundary for River Rch & Prof#=A104-04-00,A104-04-00_0007      , 3
Up Type= 0
Dn Type= 1
Dn Known WS=4.1
Boundary for River Rch & Prof#=A104-04-00,A104-04-00_0007      , 4
Up Type= 0
Dn Type= 1
Dn Known WS=5.3
DSS Import GetInterval= 0
DSS Import GetPeak= 0
DSS Import FillOption= 0

--- A104_04_00.f02 (steady flow) ---

Flow Title=Floodway
Version=Version 3.0.1  Mar 2001
Number of Profiles= 2
Profile Names=1PCT_100yr, 1PCTFloodway_100yrFW
River Rch & RM=A104-04-00,A104-04-00_0007     ,4000.427
    1630    1630
River Rch & RM=A104-04-00,A104-04-00_0007      ,2575.275
    1749    1749
Boundary for River Rch & Prof#=A104-04-00,A104-04-00_0007      , 1
Up Type= 0
Dn Type= 1
Dn Known WS=4.1
Boundary for River Rch & Prof#=A104-04-00,A104-04-00_0007      , 2
Up Type= 0
Dn Type= 1
Dn Known WS=5.1
DSS Import GetInterval= 0
DSS Import GetPeak= 0
DSS Import FillOption= 0

--- A104_04_00.g01 (geometry) ---

Geom Title=A104-04-00 June 2007
Version=Version 3.0.1  Mar 2001

River Reach=A104-04-00,A104-04-00_0007
Reach XY= 30
       3218806.5       13793143.        3218931.       13792898.
      3219099.25       13792607.        3219766.       13791311.
      3220168.25    13790545.001      3220226.75       13790415.
       3220255.5       13790319.      3220262.25       13790179.
        3220277.       13790112.      3220318.25    13790028.999
      3220443.25    13789801.001      3220671.75    13789340.999
      3221427.75       13787898.        3221637.       13787506.
        3221696.    13787412.999      3221864.75       13787426.
      3222070.25       13787463.       3222330.5       13787562.
      3222569.75       13787694.      3222996.75       13787872.
       3223290.5       13787952.        3223686.    13787993.001
       3224185.5       13788056.      3224355.75       13788052.
       3224539.5       13788018.        3224711.    13787972.999
       3224903.5       13787910.       3225094.5       13787822.
      3225299.25       13787695.       3225502.5       13787540.

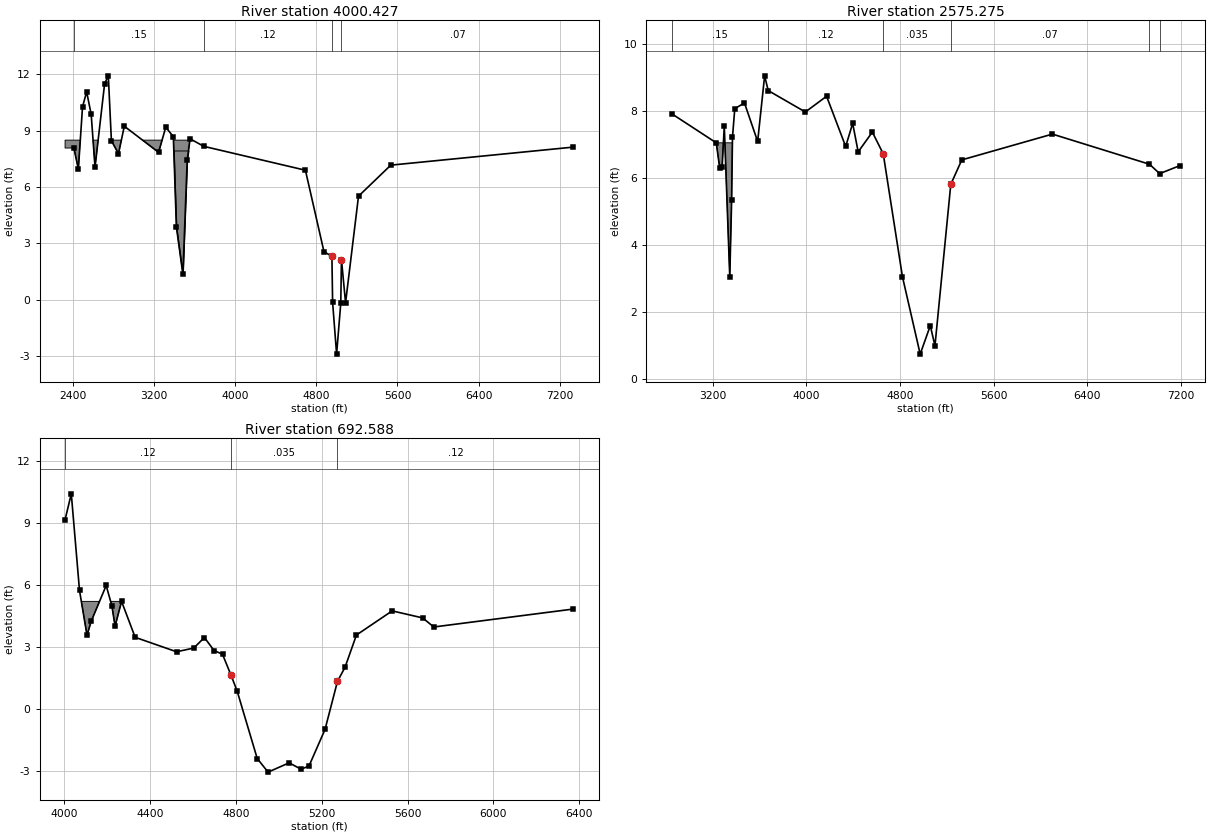
Type RM Length L Ch R = 1 ,4000.427,1374.93,1425.15,1465.56
XS GIS Cut Line= 6
     3221726.568    13789966.049     3221750.564    13789726.087
     3221702.108    13787951.939     3221670.328    13787569.047
     3221823.518    13787218.869      3222271.75    13785119.903
#Sta/Elev= 30
 2407.46    8.07 2451.39    6.95  2492.5   10.26 2533.07   11.06 2577.99    9.86
 2615.74    7.05 2710.39   11.49 2746.92   11.91 2777.35    8.46 2847.38    7.77
 2904.64    9.23 3243.21    7.84 3313.59    9.18 3388.62    8.67 3418.63    3.88
 3482.88    1.35 3525.33    7.44  3553.9    8.56 3688.94    8.16 4691.55    6.89
 4874.52    2.56  4952.9    2.31 4959.89    -.14 4999.26   -2.89  5040.4    -.18
  5047.1    2.14 5087.61    -.16 5215.36    5.51 5534.02    7.16 7336.24    8.12
#Mann= 4 ,-1 , 0
 2407.46     .15       0 3688.94     .12       0  4952.9    .035       0
  5047.1     .07       0
#Block Obstruct= 2 ,-1
  2320.4 3567.45    8.49 3337.31  3587.6    7.94
Bank Sta=4952.9,5047.1
XS Rating Curve= 0
Exp/Cntr=.3,.1

Type RM Length L Ch R = 1 ,2575.275,2995.68,1882.69,1521.64
XS GIS Cut Line= 6
     3222430.456    13789942.053     3222921.362    13788315.252
      3222983.17    13788085.431     3223156.225    13787690.975
     3223295.427    13787260.259     3223734.197     13785802.85
#Sta/Elev= 30
 2848.21    7.91 3229.51    7.04 3258.67     6.3 3279.72    6.32 3298.08    7.54
 3345.09    3.03 3360.75    5.32 3368.21    7.21 3387.79    8.06 3470.43    8.23
 3583.19    7.08 3642.76    9.04 3673.32     8.6 3990.51    7.96 4172.03    8.43
 4335.01    6.93 4394.85    7.62 4441.85    6.77  4562.9    7.36    4656    6.71
    4820    3.04 4971.62     .73 5057.76    1.58 5097.76     .98    5233     5.8
    5327    6.53 6101.09     7.3 6930.32     6.4 7017.17    6.12 7190.88    6.36
#Mann= 6 ,-1 , 0
 2848.21     .15       0 3673.32     .12       0    4656    .035       0
    5233     .07       0 6930.32     .12       0 7017.17     .07       0
#Block Obstruct= 1 ,-1
 3206.92 3415.84    7.04
Bank Sta=4656,5233
XS Rating Curve= 0
Exp/Cntr=.3,.1

Type RM Length L Ch R = 1 ,692.588 ,431.28,692.59,290.15
XS GIS Cut Line= 6
     3225114.993     13788825.84       3225048.1     13788445.39
     3224999.107    13788237.636     3224808.079    13787466.668
     3224680.192    13787065.735     3224316.465    13786647.658
#Sta/Elev= 30
 4003.83    9.16 4032.75   10.41 4071.02    5.73 4106.02    3.56 4125.69    4.24
 4195.32    5.97 4221.74    4.99 4236.83       4 4267.06     5.2 4330.33    3.46
 4523.29    2.76 4603.57    2.94 4652.94    3.45 4698.14    2.82 4737.41    2.64
 4777.29    1.62 4805.84     .85 4899.13   -2.41 4949.65   -3.07 5047.86   -2.62
 5103.99   -2.93 5140.57   -2.77 5215.16      -1 5273.24    1.33 5308.43    2.01
  5361.4    3.57    5528    4.74 5669.86     4.4 5721.98    3.96 6372.84    4.83
#Mann= 3 ,-1 , 0
 4003.83     .12       0 4777.29    .035       0 5273.24     .12       0
#XS Ineff= 1 ,-1
    5555    6120     4.3
Permanent Ineff=
       F
#Block Obstruct= 1 ,-1
 4032.78 4267.07     5.2
Bank Sta=4777.29,5273.24
XS Rating Curve= 0
Exp/Cntr=.3,.1

Chan Stop Cuts=-1

--- A104_04_00.g02 (geometry) ---

Geom Title=A104-04-00 June 2007 (Floodway)
Version=Version 3.0.1  Mar 2001

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
River Reach=A104-04-00,A104-04-00_0007